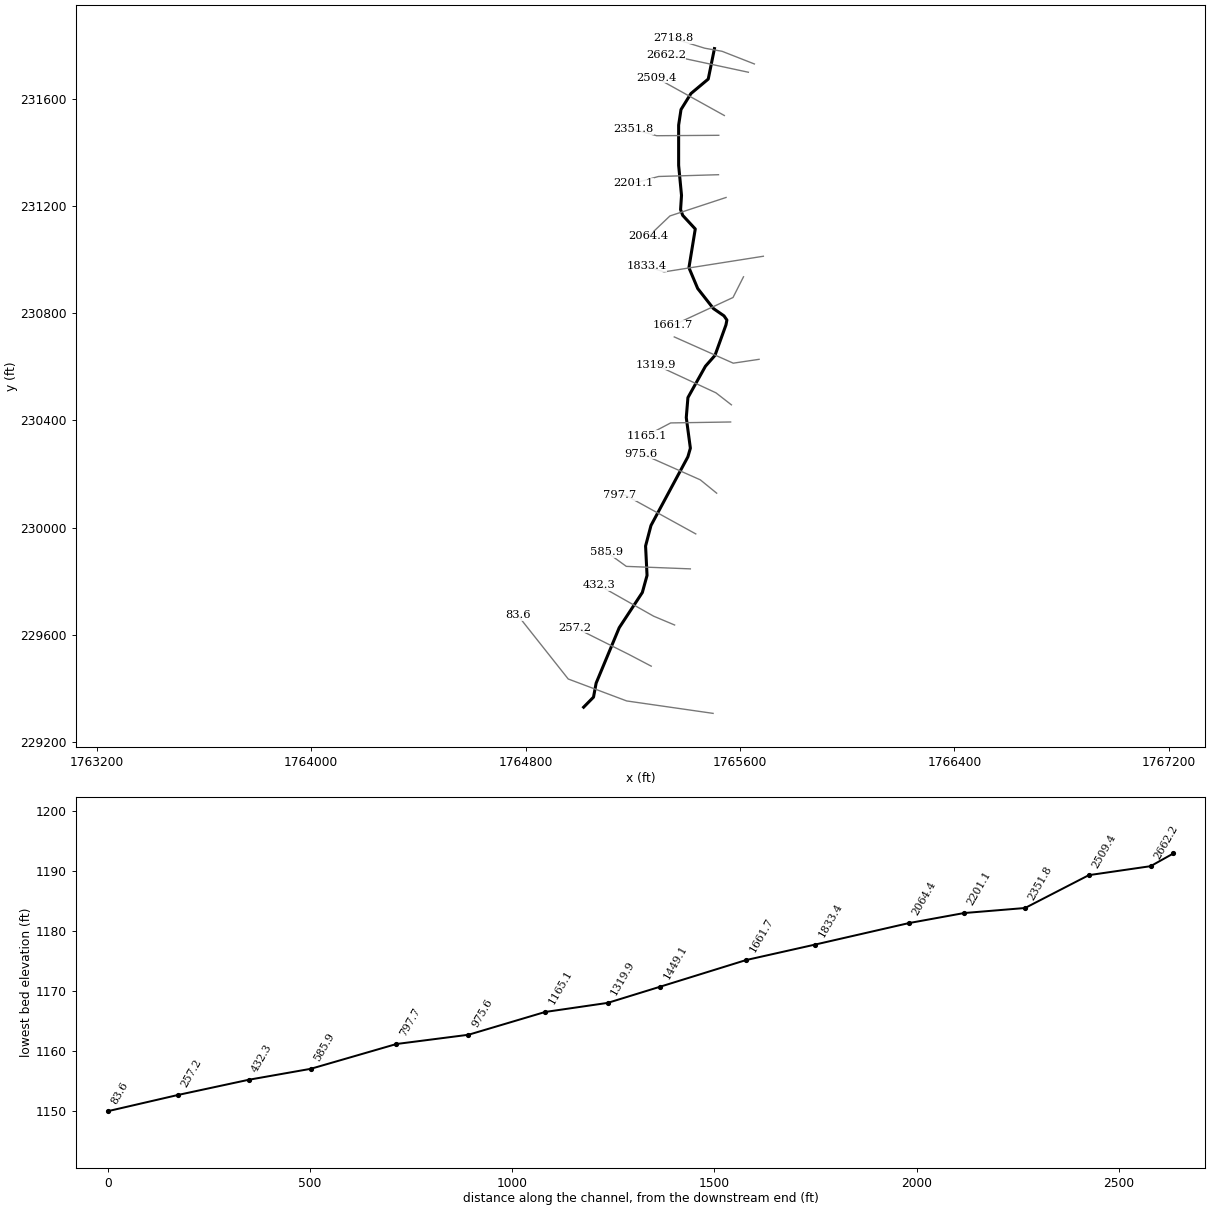
--- CedarCr1.prj (project) ---

Proj Title=CedarCr1
Current Plan=p01
Default Exp/Contr=0,0
English Units
Geom File=g01
Flow File=f01
Plan File=p01
BEGIN DESCRIPTION:
END DESCRIPTION:
DSS Export Rating Curves= 0
DSS Export Rating Curve Sorted= 0
DSS Export Volume Flow Curves= 0
DXF OffsetX= 0
DXF OffsetY= 0
DXF ScaleX= 0
DXF ScaleY= 0

--- CedarCr1.p01 (plan) ---

Plan Title=Floodplain
Program Version=4.00
Geom File=g01
Flow File=f01
K Sum by GR=0
Std Step Tol=0.01
Critical Tol=0.01
Num of Std Step Trials=20
Max Error Tol=0.3
Flow Tol Ratio=0.001
Split Flow NTrial=30
Split Flow Tol=0.02
Split Flow Ratio=0.02
Log Output Level=0
Friction Slope Method=1
Unsteady Friction Slope Method=2
Unsteady Bridges Friction Slope Method=1
Global Log Level=0
CheckData=False
Run HTab=0
Run UNet=0
Run PostProcess=0
UNET Theta=0
UNET Theta Warmup=0
UNET ZTol=0
UNET ZSATol=0
UNET MxIter=0
UNET MaxInSteps=0
UNET DtIC=0
UNET DtMin=0
UNET MaxCRTS=0
UNET WFStab=0
UNET SFStab=0
UNET WFX=0
UNET SFX=0
UNET DSS MLevel=0
UNET DZMax Abort=0
UNET Convert EG Bridges=0
UNET Use Existing IB Tables=0
UNET Froude Limit=0
UNET Froude Power=0
Write IC File=0
Echo Input=False
Echo Output=False
Write Detailed=0

--- CedarCr1.f01 (steady flow) ---

Flow Title=NFF Regression Equation
Program Version=4.00
Number of Profiles=1
Profile Names=P100yr
River Rch & RM=CedarCr1,Main      ,2718.8
550.1296
River Rch & RM=CedarCr1,Main      ,2662.2
588.1694
River Rch & RM=CedarCr1,Main      ,2064.4
601.7969
River Rch & RM=CedarCr1,Main      ,1165.1
658.5046
River Rch & RM=CedarCr1,Main      ,257.2
687.2736
Boundary for River Rch & Prof#=CedarCr1,Main      ,1
Up Type=0
Dn Type=3
Dn Slope=0.013803

--- CedarCr1.g01 (geometry) ---

Geom Title=USGS 10m DEM
Program Version=4.00

River Reach=CedarCr1     ,Main
Reach XY= 30
     1765504.665      231786.622     1765481.498      231672.957
     1765417.019      231618.956     1765379.943      231559.313
     1765371.078      231501.281     1765371.078      231351.367
     1765381.800      231239.190     1765378.331      231186.140
     1765386.391      231164.378     1765433.118      231113.828
     1765409.466      230969.369     1765442.175      230891.745
     1765500.760      230817.050     1765540.304      230789.711
     1765551.045      230774.088     1765547.627      230756.024
     1765506.618      230642.273     1765471.020      230601.797
     1765405.735      230484.929     1765399.567      230410.389
     1765414.836      230296.137     1765405.560      230263.916
     1765267.911      230007.783     1765247.761      229931.214
     1765253.240      229821.604     1765235.671      229757.927
     1765149.431      229626.550     1765063.329      229419.813
     1765053.566      229367.575     1765016.707      229330.092

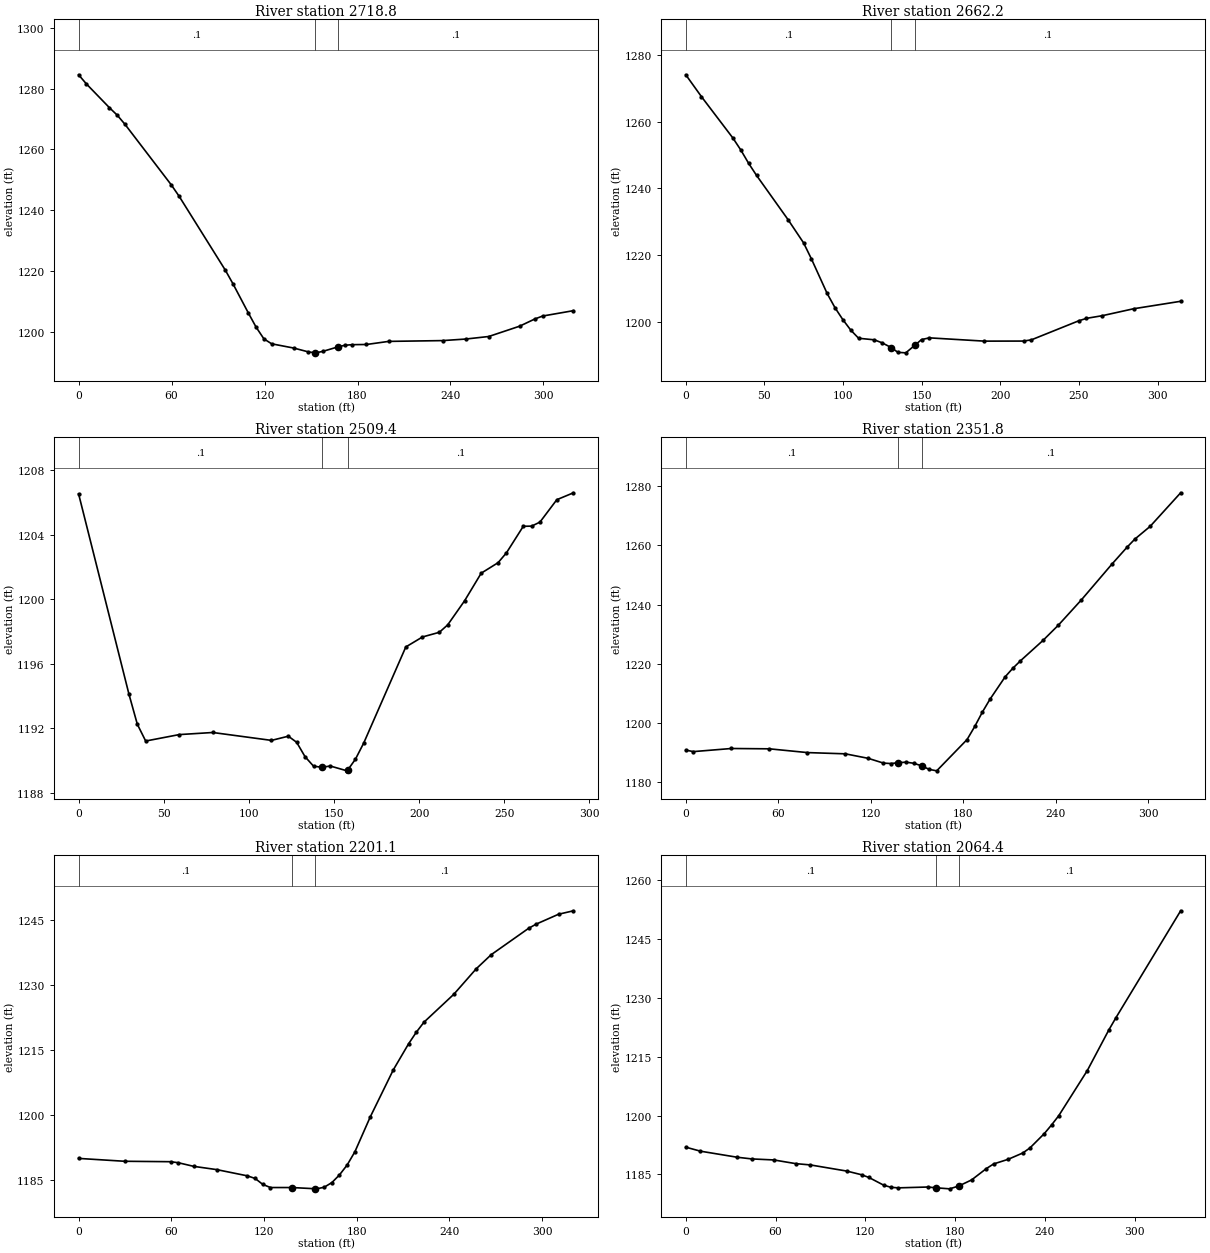
Type RM Length L Ch R = 1 ,2718.8,57.3,56.5,65.4
XS GIS Cut Line= 4
     1765653.574      231729.291     1765532.972      231776.571
     1765468.410      231788.049     1765349.754      231824.874
#Sta/Elev= 30
       0 1284.54     5.0 1281.55    19.9 1273.70    24.9 1271.26    29.9 1268.25
    59.8 1248.30    64.8 1244.60    94.7 1220.20    99.6 1215.74   109.6 1206.06
   114.6 1201.40   119.6 1197.58   124.6 1195.95   138.9 1194.55   148.3 1193.29
   152.3 1193.02   153.0 1192.98   157.6 1193.46   167.3 1194.93   171.7 1195.46
   176.4 1195.67   185.8 1195.73   200.1 1196.75   234.9 1197.01   249.8 1197.52
   264.7 1198.36   284.6 1201.75   294.5 1204.14   299.5 1205.10   319.4 1206.87
#Mann= 3 , 0 , 0
       0     0.1       0   152.3   0.045       0   167.3     0.1       0
Bank Sta=   152.3,   167.3
Exp/Cntr=0.3,0.1

Type RM Length L Ch R = 1 ,2662.2,159.6,152.8,146.1
XS GIS Cut Line= 2
     1765631.249      231698.379     1765323.504      231764.376
#Sta/Elev= 30
       0 1273.97    10.0 1267.41    30.0 1255.04    35.0 1251.48    40.0 1247.48
    45.0 1243.89    65.0 1230.69    74.9 1223.73    79.9 1218.93    89.9 1208.59
    94.9 1204.33    99.9 1200.76   104.9 1197.65   109.9 1195.21   119.9 1194.74
   124.9 1193.83   130.6 1192.44   134.9 1191.00   139.9 1190.85   145.6 1193.09
   149.9 1194.81   154.9 1195.33   189.8 1194.35   214.8 1194.37   219.8 1194.74
   249.8 1200.41   254.8 1201.16   264.8 1201.95   284.8 1204.03   314.7 1206.26
#Mann= 3 , 0 , 0
       0     0.1       0   130.6   0.045       0   145.6     0.1       0
Bank Sta=   130.6,   145.6
Exp/Cntr=0.3,0.1

Type RM Length L Ch R = 1 ,2509.4,146,157.6,169.2
XS GIS Cut Line= 2
     1765541.580      231536.975     1765287.349      231678.008
#Sta/Elev= 30
       0 1206.54    29.6 1194.10    34.5 1192.24    39.4 1191.20    59.1 1191.60
    78.8 1191.73   113.3 1191.24   123.2 1191.50   128.1 1191.12   133.0 1190.23
   138.0 1189.64     143 1189.57   147.8 1189.65   157.7 1189.35     158 1189.39
   162.6 1190.07   167.5 1191.08   192.2 1197.04   202.0 1197.66   211.9 1197.95
   216.8 1198.41   226.7 1199.90   236.5 1201.62   246.4 1202.27   251.3 1202.88
   261.2 1204.53   266.1 1204.54   271.0 1204.79   280.9 1206.18   290.7 1206.61
#Mann= 3 , 0 , 0
       0     0.1       0     143   0.045       0     158     0.1       0
Bank Sta=     143,     158
Exp/Cntr=0.3,0.1

Type RM Length L Ch R = 1 ,2351.8,150.2,150.7,151.2
XS GIS Cut Line= 3
     1765520.808      231463.164     1765289.071      231461.652
     1765203.056      231484.995
#Sta/Elev= 30
       0 1190.87     4.9 1190.36    29.6 1191.41    54.2 1191.30    78.9 1190.03
   103.5 1189.61   118.3 1188.09   128.2 1186.48   133.1 1186.33   137.9 1186.63
   143.0 1186.80   147.9 1186.41   152.9 1185.57   157.8 1184.37   162.7 1183.87
   182.4 1194.43   187.4 1198.86   192.3 1203.68   197.2 1207.99   207.1 1215.61
   212.0 1218.46   217.0 1221.00   231.7 1227.92   241.6 1233.04   256.5 1241.56
   276.3 1253.62   286.2 1259.39   291.2 1262.09   301.1 1266.38   320.9 1277.72
#Mann= 3 , 0 , 0
       0     0.1       0   137.9   0.045       0   152.9     0.1       0
Bank Sta=   137.9,   152.9
Exp/Cntr=0.3,0.1

Type RM Length L Ch R = 1 ,2201.1,130.3,136.7,148.4
XS GIS Cut Line= 3
     1765519.719      231316.225     1765296.244      231309.573
     1765202.828      231284.226
#Sta/Elev= 30
       0 1190.04    29.8 1189.38    59.6 1189.28    64.6 1189.04    74.5 1188.21
    89.4 1187.46   109.3 1186.02   114.3 1185.42   119.2 1184.06   124.2 1183.33
   138.2 1183.33   153.2 1183.05   154.0 1183.03   159.0 1183.40   164.0 1184.48
   168.9 1186.24   173.9 1188.54   178.9 1191.59   188.8 1199.58   203.7 1210.41
   213.6 1216.42   218.6 1219.09   223.6 1221.42   242.9 1227.84   257.4 1233.71
   267.1 1236.96   291.3 1243.03   296.2 1244.00   310.7 1246.28   320.4 1247.08
#Mann= 3 , 0 , 0
       0     0.1       0   138.2   0.045       0   153.2     0.1       0
Bank Sta=   138.2,   153.2
Exp/Cntr=0.3,0.1

Type RM Length L Ch R = 1 ,2064.4,234.7,230.9,227.2
XS GIS Cut Line= 3
     1765547.985      231231.300     1765338.642      231162.422
     1765258.728      231086.378
#Sta/Elev= 30
       0 1191.95     9.8 1190.93    34.3 1189.39    44.1 1188.96    58.8 1188.70
    73.5 1187.76    83.3 1187.43   107.7 1185.86   117.5 1184.93   122.4 1184.24
   132.2 1182.29   137.1 1181.74   142.0 1181.60   161.6 1181.81   167.4 1181.61
   176.3 1181.35   182.4 1182.07   191.0 1183.62   200.8 1186.49   205.7 1187.68
   215.5 1188.87   225.2 1190.47   230.0 1191.76   239.6 1195.41   244.4 1197.59
   249.2 1199.94   268.3 1211.43   282.7 1221.77   287.5 1224.92   330.7 1252.08
#Mann= 3 , 0 , 0
       0     0.1       0   167.4   0.045       0   182.4     0.1       0
Bank Sta=   167.4,   182.4
Exp/Cntr=0.3,0.1

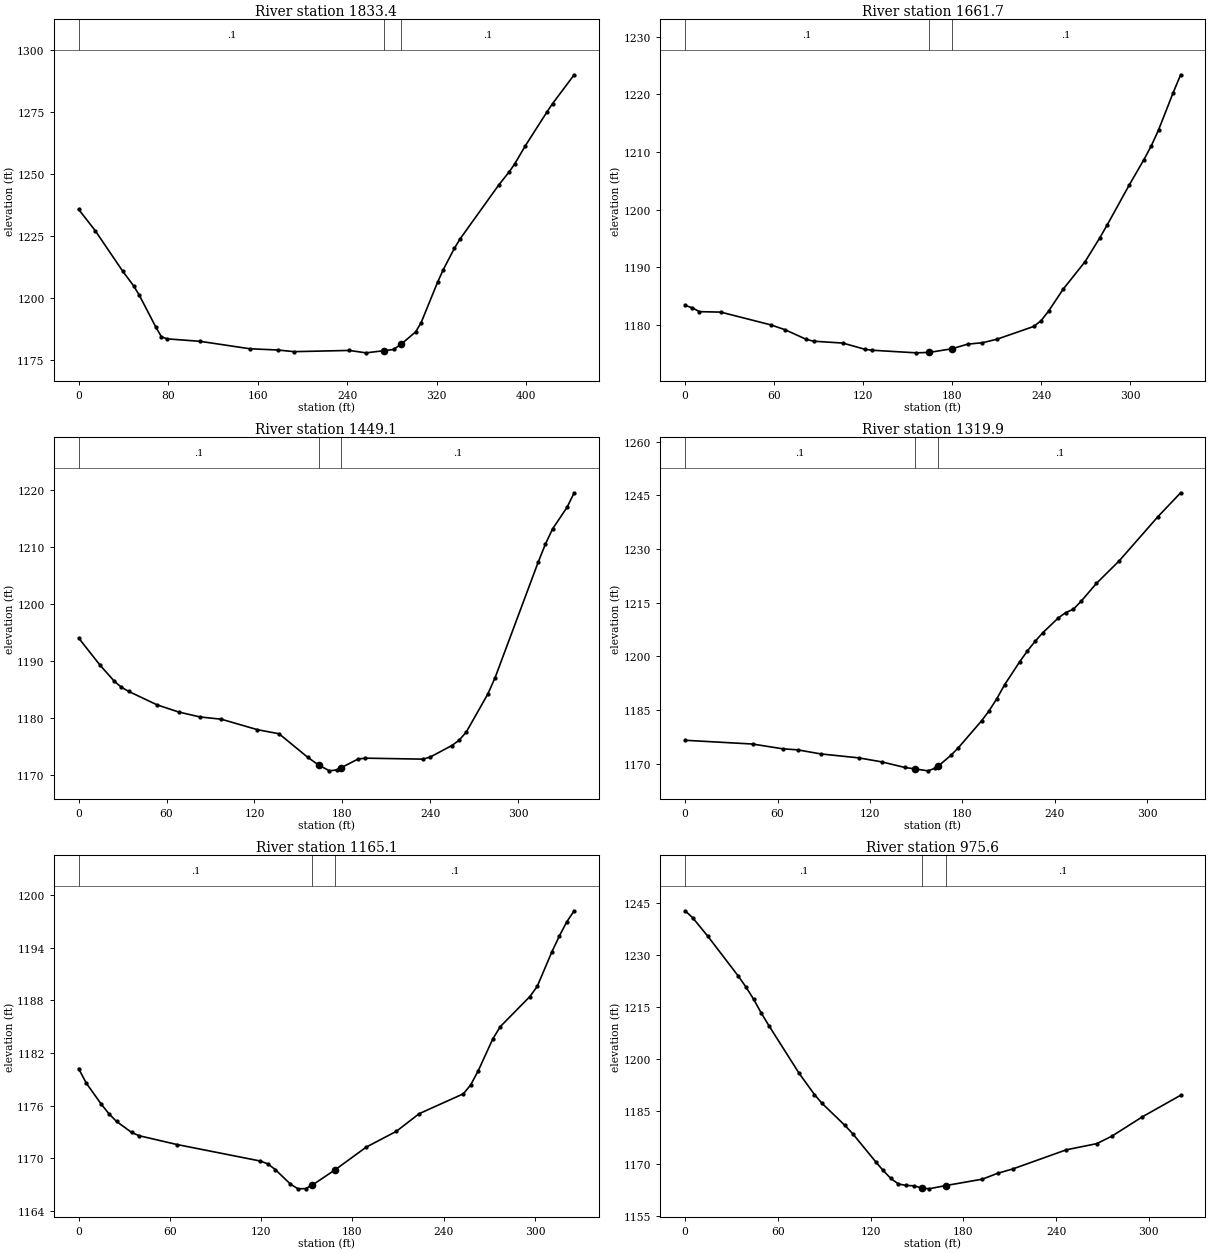
Type RM Length L Ch R = 1 ,1833.4,166.3,171.7,178
XS GIS Cut Line= 3
     1765687.083      231012.080     1765316.533      230953.712
     1765252.353      230974.825
#Sta/Elev= 30
       0 1235.64    14.8 1227.08    39.5 1210.63    49.4 1204.64    54.3 1200.94
    69.1 1188.05    74.0 1184.24    79.0 1183.42   108.6 1182.42   153.0 1179.42
   177.7 1178.93   192.5 1178.26   241.8 1178.75   256.7 1177.78   273.1 1178.66
   281.3 1179.14   288.1 1181.26   301.1 1186.24   306.0 1189.98   320.8 1206.40
   325.8 1211.37   335.6 1219.87   340.6 1223.62   375.1 1245.35   384.8 1250.87
   389.6 1254.01   399.2 1261.38   418.6 1275.08   423.4 1278.30   442.7 1289.93
#Mann= 3 , 0 , 0
       0     0.1       0   273.1   0.045       0   288.1     0.1       0
Bank Sta=   273.1,   288.1
Exp/Cntr=0.3,0.1

Type RM Length L Ch R = 1 ,1661.7,231.7,212.6,192.6
XS GIS Cut Line= 3
     1765613.004      230935.392     1765573.884      230858.200
     1765349.593      230754.235
#Sta/Elev= 30
       0 1183.40     4.8 1182.99     9.6 1182.32    24.0 1182.24    57.7 1180.03
    67.3 1179.19    81.7 1177.51    86.5 1177.20   106.3 1176.87   121.2 1175.79
   126.1 1175.63   155.8 1175.18   164.6 1175.26   179.6 1175.88   190.4 1176.69
   200.3 1176.93   210.2 1177.55   234.9 1179.76   239.8 1180.75   244.8 1182.40
   254.6 1186.19   269.5 1191.01   279.4 1195.14   284.3 1197.34   299.1 1204.24
   309.0 1208.64   314.0 1211.05   318.9 1213.80   328.8 1220.30   333.8 1223.38
#Mann= 3 , 0 , 0
       0     0.1       0   164.6   0.045       0   179.6     0.1       0
Bank Sta=   164.6,   179.6
Exp/Cntr=0.3,0.1

Type RM Length L Ch R = 1 ,1449.1,129.5,129.2,128.9
XS GIS Cut Line= 3
     1765671.149      230627.620     1765574.768      230613.230
     1765354.791      230711.146
#Sta/Elev= 30
       0 1194.00    14.6 1189.24    24.4 1186.41    29.2 1185.37    34.1 1184.65
    53.6 1182.28    68.2 1181.04    82.8 1180.17    97.4 1179.77   122.0 1177.94
   136.8 1177.22   156.4 1173.09     164 1171.72   171.2 1170.73   176.1 1170.89
     179 1171.26   190.8 1172.81   195.7 1172.95   235.0 1172.78   240.0 1173.15
   254.7 1175.16   259.6 1176.07   264.5 1177.50   279.3 1184.20   284.2 1187.03
   313.7 1207.32   318.6 1210.46   323.5 1213.12   333.3 1216.87   338.2 1219.43
#Mann= 3 , 0 , 0
       0     0.1       0     164   0.045       0     179     0.1       0
Bank Sta=     164,     179
Exp/Cntr=0.3,0.1

Type RM Length L Ch R = 1 ,1319.9,144.6,154.9,165.1
XS GIS Cut Line= 3
     1765567.866      230457.828     1765510.210      230502.685
     1765284.750      230607.329
#Sta/Elev= 30
       0 1176.58    43.8 1175.53    63.3 1174.20    73.0 1173.91    88.0 1172.77
   112.8 1171.66   127.7 1170.54   142.6 1168.98   149.3 1168.57   157.6 1168.04
   162.5 1168.81   164.3 1169.38   172.5 1172.37   177.4 1174.52   192.4 1182.01
   197.3 1184.82   202.3 1188.20   207.3 1192.07   217.2 1198.55   222.2 1201.58
   227.2 1204.26   232.1 1206.61   242.1 1210.73   247.0 1212.26   252.0 1213.20
   257.0 1215.42   266.9 1220.39   281.8 1226.75   306.7 1238.99   321.6 1245.74
#Mann= 3 , 0 , 0
       0     0.1       0   149.3   0.045       0   164.3     0.1       0
Bank Sta=   149.3,   164.3
Exp/Cntr=0.3,0.1

Type RM Length L Ch R = 1 ,1165.1,199.3,189.5,179.7
XS GIS Cut Line= 3
     1765565.040      230393.907     1765341.296      230390.370
     1765251.139      230342.872
#Sta/Elev= 30
       0 1180.22     5.0 1178.57    14.9 1176.16    19.9 1175.08    24.9 1174.20
    34.8 1172.95    39.8 1172.57    64.6 1171.57   119.4 1169.69   124.3 1169.37
   129.3 1168.71   139.2 1167.06   144.2 1166.52   149.2 1166.55   153.6 1166.95
   168.6 1168.69   189.0 1171.27   208.8 1173.07   223.8 1175.08   252.9 1177.35
   257.7 1178.37   262.6 1179.96   272.3 1183.63   277.2 1185.01   296.6 1188.43
   301.4 1189.58   311.1 1193.54   316.0 1195.34   320.8 1196.93   325.7 1198.20
#Mann= 3 , 0 , 0
       0     0.1       0   153.6   0.045       0   168.6     0.1       0
Bank Sta=   153.6,   168.6
Exp/Cntr=0.3,0.1

Type RM Length L Ch R = 1 ,975.6,179.8,177.9,175.9
XS GIS Cut Line= 3
     1765512.911      230128.367     1765451.841      230178.122
     1765230.822      230276.246
#Sta/Elev= 30
       0 1242.68     4.9 1240.68    14.8 1235.31    34.5 1223.85    39.4 1220.74
    44.3 1217.28    49.2 1213.33    54.2 1209.66    73.8 1195.92    83.7 1189.83
    88.6 1187.31   103.4 1180.96   108.4 1178.60   123.2 1170.56   128.1 1168.02
   133.1 1165.71   138.0 1164.12   142.9 1163.71   147.9 1163.59   153.5 1162.95
   157.7 1162.72   168.5 1163.65   192.3 1165.50   202.2 1167.19   212.0 1168.44
   246.6 1173.94   266.3 1175.71   276.2 1177.89   295.9 1183.45   320.6 1189.63
#Mann= 3 , 0 , 0
       0     0.1       0   153.5   0.045       0   168.5     0.1       0
Bank Sta=   153.5,   168.5
Exp/Cntr=0.3,0.1

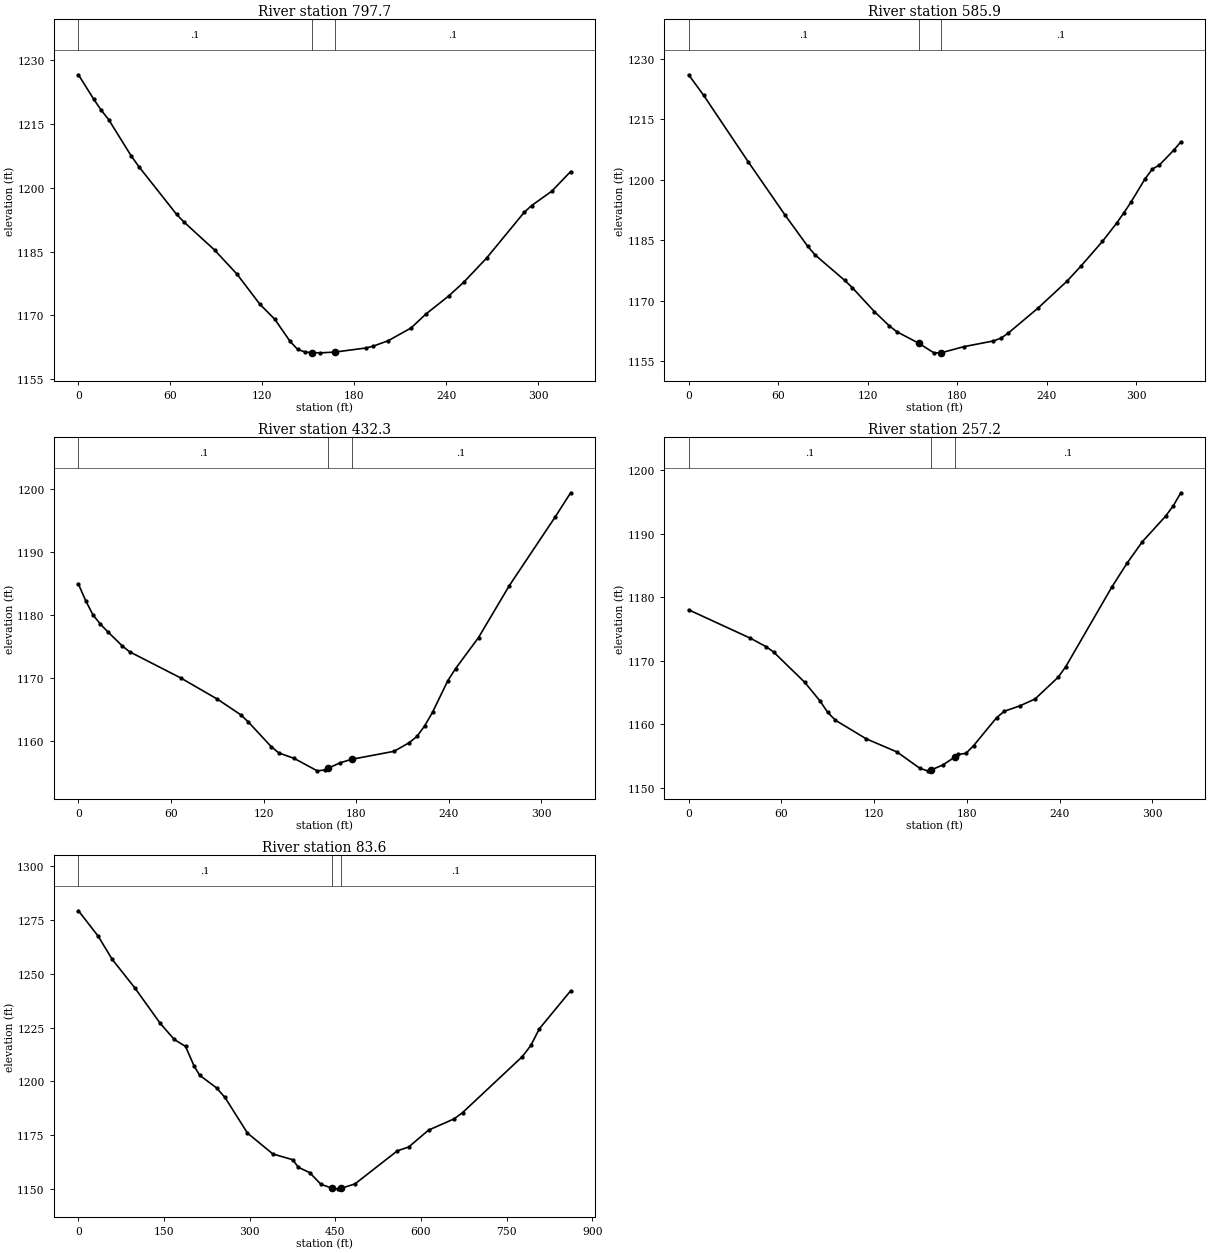
Type RM Length L Ch R = 1 ,797.7,201.2,211.9,222.5
XS GIS Cut Line= 3
     1765434.957      229976.431     1765171.497      230121.522
     1765151.109      230120.979
#Sta/Elev= 30
       0 1226.54     9.9 1220.84    14.8 1218.24    19.7 1216.01    34.5 1207.43
    39.4 1204.96    64.1 1193.70    69.0 1191.88    88.8 1185.36   103.5 1179.66
   118.3 1172.65   128.2 1169.04   138.1 1163.88   143.0 1162.00   147.9 1161.37
   152.2 1161.23   157.8 1161.18   167.2 1161.35   187.4 1162.31   192.3 1162.74
   202.2 1164.04   217.0 1167.01   226.8 1170.32   241.6 1174.54   251.5 1177.80
   266.3 1183.44   290.9 1194.21   295.8 1195.81   308.9 1199.18   321.2 1203.79
#Mann= 3 , 0 , 0
       0     0.1       0   152.2   0.045       0   167.2     0.1       0
Bank Sta=   152.2,   167.2
Exp/Cntr=0.3,0.1

Type RM Length L Ch R = 1 ,585.9,164.3,153.6,142.9
XS GIS Cut Line= 3
     1765414.765      229846.014     1765175.919      229855.328
     1765102.450      229908.477
#Sta/Elev= 30
       0 1225.98    10.0 1220.92    39.8 1204.47    64.7 1191.14    79.7 1183.50
    84.7 1181.32   104.6 1175.00   109.6 1173.22   124.5 1167.24   134.4 1163.74
   139.4 1162.29   154.1 1159.43   164.3 1157.04   169.1 1157.04   184.2 1158.56
   204.2 1159.99   209.2 1160.68   214.1 1161.93   234.0 1168.12   253.4 1174.78
   262.9 1178.59   277.2 1184.67   286.8 1189.24   291.5 1191.72   296.3 1194.40
   305.8 1200.21   310.6 1202.59   315.4 1203.62   324.9 1207.26   329.7 1209.33
#Mann= 3 , 0 , 0
       0     0.1       0   154.1   0.045       0   169.1     0.1       0
Bank Sta=   154.1,   169.1
Exp/Cntr=0.3,0.1

Type RM Length L Ch R = 1 ,432.3,174,175.1,176.2
XS GIS Cut Line= 3
     1765356.037      229636.648     1765277.621      229669.611
     1765074.085      229784.789
#Sta/Elev= 30
       0 1184.84     4.7 1182.20     9.4 1179.96    14.2 1178.50    18.9 1177.30
    28.4 1175.03    33.1 1174.11    66.2 1169.96    90.0 1166.59   105.0 1164.13
   109.9 1163.01   124.9 1159.05   129.8 1158.06   139.8 1157.18   154.7 1155.21
   159.7 1155.35     162 1155.65   169.6 1156.49     177 1157.04   204.5 1158.31
   214.4 1159.69   219.4 1160.70   224.4 1162.38   229.4 1164.50   239.3 1169.51
   244.3 1171.42   259.2 1176.36   279.1 1184.58   309.0 1195.55   318.9 1199.34
#Mann= 3 , 0 , 0
       0     0.1       0     162   0.045       0     177     0.1       0
Bank Sta=     162,     177
Exp/Cntr=0.3,0.1

Type RM Length L Ch R = 1 ,257.2,171.2,173.6,175.9
XS GIS Cut Line= 3
     1765268.856      229483.110     1765184.763      229527.228
     1764984.896      229627.161
#Sta/Elev= 30
       0 1178.02    40.0 1173.54    50.0 1172.23    55.0 1171.37    75.0 1166.63
    85.0 1163.67    90.0 1161.86    95.0 1160.63   114.8 1157.72   134.7 1155.65
   149.6 1153.07   154.6 1152.67   157.1 1152.83   164.5 1153.60   172.1 1154.82
   174.4 1155.26   179.4 1155.42   184.4 1156.65   199.2 1161.03   204.2 1162.05
   214.1 1162.88   224.1 1163.98   239.0 1167.39   243.9 1169.04   273.7 1181.57
   283.7 1185.39   293.6 1188.76   308.5 1192.74   313.5 1194.38   318.4 1196.44
#Mann= 3 , 0 , 0
       0     0.1       0   157.1   0.045       0   172.1     0.1       0
Bank Sta=   157.1,   172.1
Exp/Cntr=0.3,0.1

Type RM Length L Ch R = 1 ,83.6,95.4,83.6,71.8
XS GIS Cut Line= 4
     1765499.597      229307.020     1765177.280      229353.393
     1764959.249      229435.254     1764770.879      229673.148
#Sta/Elev= 30
       0 1279.33    34.5 1267.53    59.2 1256.69    98.7 1243.46   143.1 1226.99
   167.8 1219.45   187.5 1216.23   202.3 1207.24   212.2 1202.82   241.8 1196.93
   256.6 1192.47   296.0 1175.89   340.5 1166.18   375.2 1163.51   385.1 1159.99
   404.9 1157.52   424.7 1152.05   444.3 1150.28   454.5 1149.96   459.3 1150.13
   484.2 1152.24   558.5 1167.64   578.4 1169.43   613.2 1177.29   658.0 1182.53
   672.9 1185.46   777.4 1211.49   792.3 1216.67   807.2 1224.43   862.0 1242.10
#Mann= 3 , 0 , 0
       0     0.1       0   444.3   0.045       0   459.3     0.1       0
Bank Sta=   444.3,   459.3
Exp/Cntr=0.3,0.1